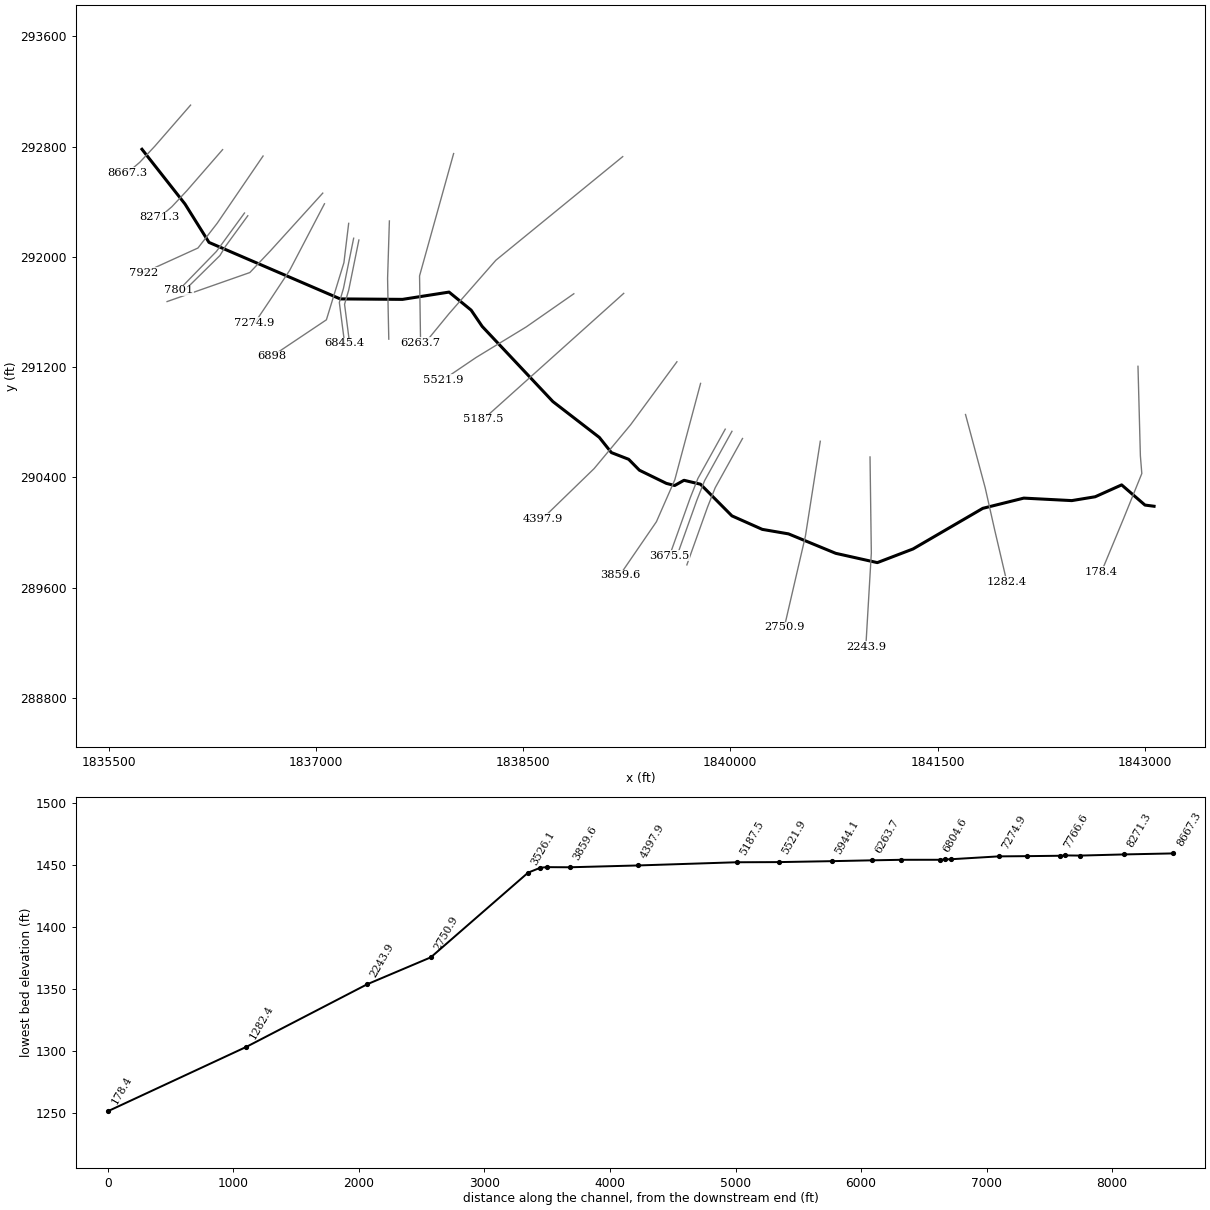
--- SwampRun.prj (project) ---

Proj Title=SwampRun
Current Plan=p01
Default Exp/Contr=0,0
English Units
Geom File=g01
Flow File=f01
Plan File=p01
BEGIN DESCRIPTION:
END DESCRIPTION:
DSS Export Rating Curves= 0
DSS Export Rating Curve Sorted= 0
DSS Export Volume Flow Curves= 0
DXF OffsetX= 0
DXF OffsetY= 0
DXF ScaleX= 0
DXF ScaleY= 0

--- SwampRun.p01 (plan) ---

Plan Title=Floodplain
Program Version=4.00
Geom File=g01
Flow File=f01
K Sum by GR=0
Std Step Tol=0.01
Critical Tol=0.01
Num of Std Step Trials=20
Max Error Tol=0.3
Flow Tol Ratio=0.001
Split Flow NTrial=30
Split Flow Tol=0.02
Split Flow Ratio=0.02
Log Output Level=0
Friction Slope Method=1
Unsteady Friction Slope Method=2
Unsteady Bridges Friction Slope Method=1
Global Log Level=0
CheckData=False
Run HTab=0
Run UNet=0
Run PostProcess=0
UNET Theta=0
UNET Theta Warmup=0
UNET ZTol=0
UNET ZSATol=0
UNET MxIter=0
UNET MaxInSteps=0
UNET DtIC=0
UNET DtMin=0
UNET MaxCRTS=0
UNET WFStab=0
UNET SFStab=0
UNET WFX=0
UNET SFX=0
UNET DSS MLevel=0
UNET DZMax Abort=0
UNET Convert EG Bridges=0
UNET Use Existing IB Tables=0
UNET Froude Limit=0
UNET Froude Power=0
Write IC File=0
Echo Input=False
Echo Output=False
Write Detailed=0

--- SwampRun.f01 (steady flow) ---

Flow Title=NFF Regression Equation
Program Version=4.10
Number of Profiles= 1
Profile Names=P100yr
River Rch & RM=SwampRun,Main            ,8667.3
     358
River Rch & RM=SwampRun,Main            ,7497.9
     378
River Rch & RM=SwampRun,Main            ,6898
     538
River Rch & RM=SwampRun,Main            ,6263.7
     544
River Rch & RM=SwampRun,Main            ,5944.1
     763
River Rch & RM=SwampRun,Main            ,3859.6
     812
River Rch & RM=SwampRun,Main            ,178.4
     885
Boundary for River Rch & Prof#=SwampRun,Main            , 1
Up Type= 0
Dn Type= 3
Dn Slope=0.04715
DSS Import GetInterval= 0
DSS Import GetPeak= 0
DSS Import FillOption= 0

--- SwampRun.g01 (geometry) ---

Geom Title=USGS 10m DEM
Program Version=4.10

River Reach=SwampRun        ,Main
Reach XY= 30
     1835741.592      292780.149     1836053.224      292382.811
     1836226.835      292104.599     1837176.197      291694.854
     1837627.258      291691.459     1837964.218      291744.299
     1838124.036      291613.485     1838204.092      291495.274
     1838715.867      290950.145     1839051.937      290690.294
     1839139.305      290580.164     1839264.399      290531.538
     1839342.028      290452.328     1839537.291       290356.81
     1839597.322      290341.458     1839664.593        290379.3
     1839784.146      290350.889     1840011.561       290121.32
      1840231.39      290023.342     1840421.341      289990.658
     1840762.871      289849.648     1841063.923      289782.186
     1841322.576      289881.358     1841827.597      290176.033
     1842124.102      290250.051     1842471.366      290231.977
     1842640.998      290259.916     1842832.306      290345.935
     1843001.093      290199.594     1843067.063      290191.016

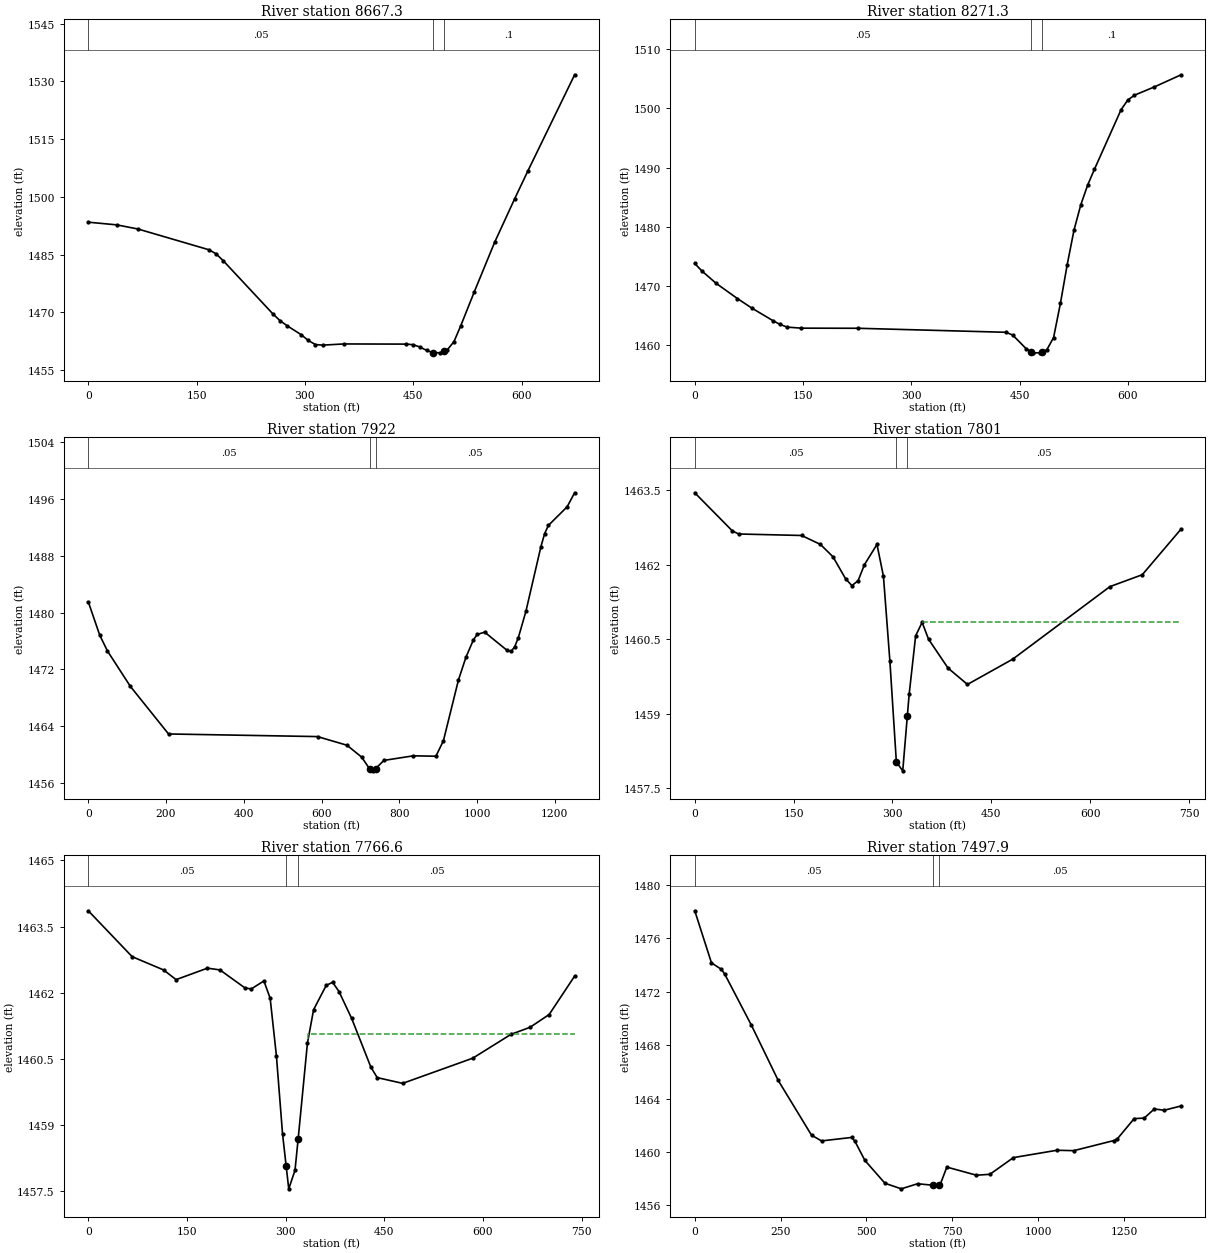
Type RM Length L Ch R = 1 ,8667.3  ,395.8,396.1,396.3
XS GIS Cut Line= 4
     1836093.487      293100.411     1835835.674      292803.536
     1835726.299      292686.349     1835635.153      292608.224
#Sta/Elev= 30
       0 1493.41    39.3 1492.72    68.8 1491.64   167.1 1486.24   176.9  1485.2
   186.8 1483.41   255.6 1469.58   265.4 1467.84   275.2 1466.51   294.9 1464.16
   304.7 1462.66   314.6  1461.6   324.4 1461.45   353.9 1461.76   440.3 1461.72
   449.8 1461.57   459.2 1460.96   468.6 1460.08   477.1 1459.52   478.1 1459.45
   487.5 1459.49   492.1 1459.83   496.9 1460.18   506.4 1462.36   515.8 1466.49
   534.6 1475.34   562.7 1488.17   590.4 1499.47   608.9 1506.79   673.5 1531.73
#Mann= 3 , 0 , 0
       0     .05       0   477.1    .045       0   492.1      .1       0
Bank Sta=477.1,492.1
XS Rating Curve= 0 ,0
Exp/Cntr=0.3,0.1

Type RM Length L Ch R = 1 ,8271.3  ,347.3,349.3,351.1
XS GIS Cut Line= 4
     1836325.258      292777.495     1836067.445       292480.62
      1835958.07      292363.432     1835866.924      292285.307
#Sta/Elev= 30
       0 1473.75     9.8 1472.49    29.5  1470.4      59 1467.82    78.6 1466.23
   108.1 1464.08     118 1463.44   127.8 1462.98   147.4  1462.8   226.1 1462.78
   430.9  1462.1   440.3 1461.63   459.2 1459.29   465.5 1458.84   468.6 1458.62
   478.1 1458.63   480.5 1458.76   487.5 1459.13   496.9  1461.2   506.4 1467.01
   515.8 1473.57   525.2 1479.41   534.6 1483.69   544.1 1487.03   553.5 1489.71
   590.4  1499.8   599.7 1501.44   608.9 1502.25   636.6 1503.66   673.5 1505.71
#Mann= 3 , 0 , 0
       0     .05       0   465.5    .045       0   480.5      .1       0
Bank Sta=465.5,480.5
XS Rating Curve= 0 ,0
Exp/Cntr=0.3,0.1

Type RM Length L Ch R = 1 ,7922    ,120.4,120.9,121.5
XS GIS Cut Line= 4
      1836618.06      292731.149     1836286.195       292243.64
     1836146.872      292063.953     1835751.907      291883.831
#Sta/Elev= 30
       0 1481.52    29.5 1476.81    49.2  1474.6   108.1 1469.61   206.4 1462.89
   589.7 1462.52   665.5  1461.3   703.4 1459.62   724.1 1457.93   731.8 1457.69
   739.1 1457.99   760.3 1459.16   836.4 1459.81   894.3 1459.75   913.6 1461.93
   952.2 1470.48   971.5  1473.7   990.8 1476.16  1000.4 1476.92  1019.7 1477.25
  1077.6 1474.67  1087.2 1474.52  1096.9 1475.16  1106.5 1476.49  1125.8 1480.17
  1164.4 1489.29    1174 1491.14  1183.7  1492.3  1231.9 1494.92  1251.2  1496.9
#Mann= 3 , 0 , 0
       0     .05       0   724.1    .045       0   739.1     .05       0
Bank Sta=724.1,739.1
XS Rating Curve= 0 ,0
Exp/Cntr=0.3,0.1

Type RM Length L Ch R = 1 ,7801    ,32.3,34.4,36.6
XS GIS Cut Line= 4
     1836483.615      292317.758     1836320.855      292094.234
     1836280.317      292039.025     1836006.428      291757.127
#Sta/Elev= 26
       0 1463.45    57.2 1462.68    66.7 1462.62   162.1 1462.59   190.7 1462.41
   209.8 1462.16   228.8 1461.72   238.4 1461.58   247.9 1461.68   257.4    1462
   276.5 1462.41   286.3 1461.77   296.1 1460.06   305.9 1458.03   315.6 1457.85
   322.6 1458.96   325.4  1459.4   335.2 1460.57     345 1460.84   354.8  1460.5
   384.3 1459.92   413.8 1459.59   482.6  1460.1     630 1461.56   679.1  1461.8
     738 1462.72
#Mann= 3 , 0 , 0
       0     .05       0   305.9    .045       0   322.6     .05       0
#XS Ineff= 2 , 0
                          344.92         1460.85
Permanent Ineff=
       F       F
Bank Sta=305.9,322.6
XS Rating Curve= 0 ,0
Exp/Cntr=0.3,0.1

Type RM Length L Ch R = 1 ,7766.6  ,274.3,268.7,263.2
XS GIS Cut Line= 4
     1836507.574      292297.966     1836344.813      292074.442
     1836306.081      292009.535     1836030.386      291737.336
#Sta/Elev= 30
       0 1463.86    66.7 1462.82   114.4 1462.52   133.5  1462.3   181.2 1462.56
   200.2 1462.52   238.4 1462.11   247.9 1462.09     267 1462.27   276.5 1461.88
     286 1460.58   295.4  1458.8   300.9 1458.07   304.8 1457.56   314.3 1457.98
  319.16  1458.7   333.2 1460.86   342.6 1461.62   361.8 1462.17   371.5 1462.24
   381.2 1462.03   400.5 1461.42   429.6 1460.32   439.3 1460.08     478 1459.95
   584.6 1460.52   642.7 1461.06   671.7 1461.22   700.8 1461.51   739.5 1462.38
#Mann= 3 , 0 , 0
       0     .05       0   300.9    .045       0  319.16     .05       0
#XS Ineff= 2 , 0
                          334.45         1461.06
Permanent Ineff=
       F       F
Bank Sta=300.9,319.16
XS Rating Curve= 0 ,0
Exp/Cntr=0.3,0.1

Type RM Length L Ch R = 1 ,7497.9  ,218.4,223,227.4
XS GIS Cut Line= 4
     1837050.178      292462.052     1836672.046      292044.422
     1836522.306      291886.001     1835923.348      291675.498
#Sta/Elev= 30
       0 1478.07    48.6 1474.17    77.7 1473.68    87.4 1473.32   165.1 1469.49
   242.8 1465.37     340 1461.26   369.1 1460.83   456.5 1461.09   466.2 1460.81
   495.4 1459.37   553.7 1457.66   601.3 1457.24   648.7 1457.62  694.33 1457.51
   711.2 1457.55     715 1457.58     734 1458.87   820.4 1458.26   859.5 1458.33
   927.9 1459.58  1054.8 1460.13  1103.7  1460.1  1220.9 1460.86  1230.7 1460.99
  1279.5  1462.5  1308.8 1462.54  1338.1 1463.22  1367.4 1463.13  1416.2 1463.45
#Mann= 3 , 0 , 0
       0     .05       0  694.33    .045       0   711.2     .05       0
Bank Sta=694.33,711.2
XS Rating Curve= 0 ,0
Exp/Cntr=0.3,0.1

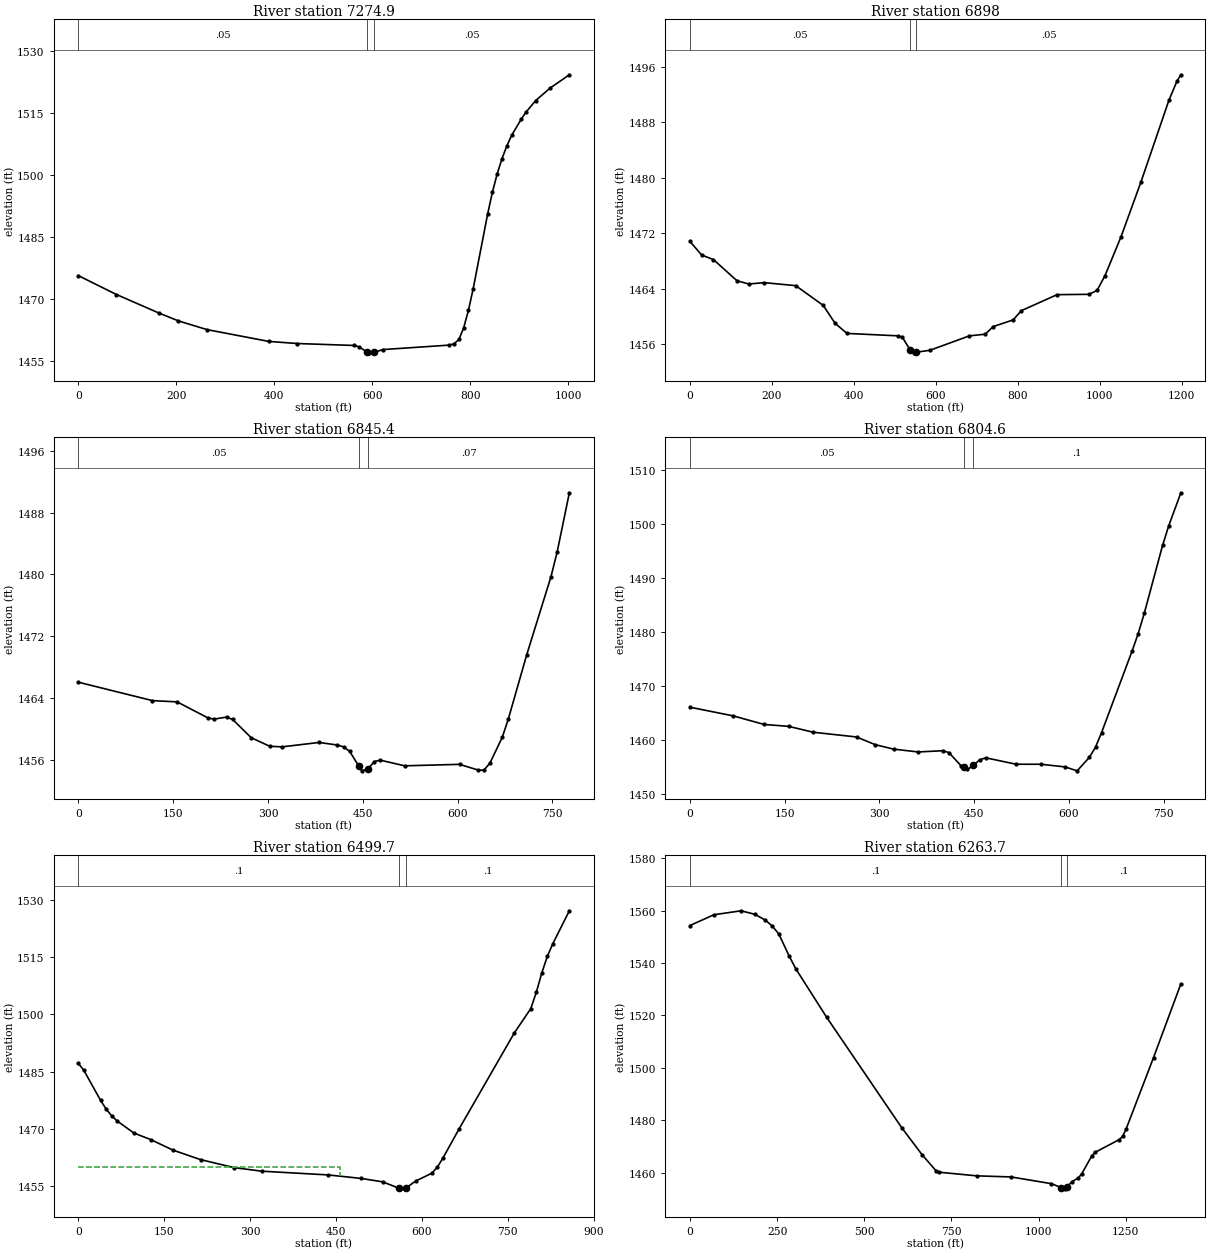
Type RM Length L Ch R = 1 ,7274.9  ,370.5,377,383.4
XS GIS Cut Line= 4
     1837062.504      292384.824     1836810.768      291902.185
     1836666.671      291683.435     1836557.296      291520.241
#Sta/Elev= 30
       0 1475.71    77.8 1471.15   165.2 1466.64   204.1 1464.79   262.4 1462.68
   388.8 1459.82   447.1 1459.31   563.8 1458.84   573.4 1458.48   588.9 1457.34
   592.8 1457.06   603.9 1457.18     622 1457.85   757.8 1458.93   767.5 1459.26
   777.2 1460.29   786.9 1463.08   796.6 1467.31   806.3  1472.5   835.8 1490.56
   845.6 1495.87   855.4 1500.31   865.2 1503.97     875 1507.04   884.9 1509.61
   904.5 1513.52   914.3 1515.24     934 1518.02   963.5 1521.04  1002.8 1524.25
#Mann= 3 , 0 , 0
       0     .05       0   588.9    .045       0   603.9     .05       0
Bank Sta=588.9,603.9
XS Rating Curve= 0 ,0
Exp/Cntr=0.3,0.1

Type RM Length L Ch R = 1 ,6898    ,52.3,52.5,52.8
XS GIS Cut Line= 4
      1837237.71      292242.857     1837203.365      291958.035
      1837076.48      291543.235     1836679.985       291277.22
#Sta/Elev= 30
       0 1470.85    28.7 1468.87    57.4 1468.22   114.8 1465.17   143.4  1464.7
   181.7 1464.89   258.2 1464.46   325.4 1461.61   354.4 1459.02   383.3 1457.57
   508.6 1457.22   518.2 1457.04   537.5 1455.19   547.2 1454.77   552.2 1454.86
   585.7 1455.14   682.1 1457.22   720.7 1457.46   740.2 1458.56   788.9 1459.52
   808.4 1460.84     896 1463.16     974 1463.21   993.5 1463.77    1013 1465.91
    1052  1471.5  1100.7 1479.41  1168.9 1491.19  1188.4 1493.93  1198.1 1494.87
#Mann= 3 , 0 , 0
       0     .05       0   537.5    .045       0   552.2     .05       0
Bank Sta=537.5,552.2
XS Rating Curve= 0 ,0
Exp/Cntr=0.3,0.1

Type RM Length L Ch R = 1 ,6845.4  ,41.3,40.9,40.7
XS GIS Cut Line= 4
     1837273.821      292134.958     1837200.091      291771.253
     1837170.143      291668.866     1837208.457      291372.111
#Sta/Elev= 30
       0 1466.06   117.2 1463.68   156.2 1463.52   205.1 1461.44   214.8 1461.29
   234.4 1461.55   244.2 1461.24   273.4 1458.89   302.7 1457.78   322.3  1457.7
   380.8 1458.27   409.9 1457.94   419.6  1457.7   429.3 1457.12   443.5 1455.25
   448.7  1454.6   458.5 1454.84   468.1  1455.8   477.8 1455.98   516.4 1455.25
   603.3 1455.44   632.2 1454.71   641.9 1454.68   651.5 1455.64   670.8 1458.93
   680.5 1461.32   709.4 1469.58     748 1479.73   757.7  1482.9     777 1490.56
#Mann= 3 , 0 , 0
       0     .05       0   443.5    .045       0   458.5     .07       0
Bank Sta=443.5,458.5
XS Rating Curve= 0 ,0
Exp/Cntr=0.3,0.1

Type RM Length L Ch R = 1 ,6804.6  ,297.5,304.8,311.9
XS GIS Cut Line= 4
     1837311.582      292121.937     1837237.851      291758.233
     1837207.903      291655.845     1837246.217       291359.09
#Sta/Elev= 30
       0 1466.08    68.4 1464.48   117.2  1462.9   156.2 1462.54   195.3 1461.45
   263.7 1460.58     293 1459.17   322.3 1458.33   361.3 1457.81   400.2 1458.04
   409.9 1457.69   429.3 1455.24   433.7 1454.94     439 1454.57   448.7 1455.32
   458.4 1456.34   468.1 1456.73   516.4 1455.54     555 1455.54   593.6 1455.05
   612.9 1454.32   632.2 1456.82   641.9 1458.69   651.5 1461.39   699.8 1476.46
   709.4 1479.66   719.1 1483.45     748 1495.97   757.7 1499.58     777 1505.71
#Mann= 3 , 0 , 0
       0     .05       0   433.7    .045       0   448.7      .1       0
Bank Sta=433.7,448.7
XS Rating Curve= 0 ,0
Exp/Cntr=0.3,0.1

Type RM Length L Ch R = 1 ,6499.7  ,236.2,236,235.8
XS GIS Cut Line= 4
     1837532.415      292260.218     1837519.394      291843.552
     1837523.735      291604.836     1837528.075      291403.013
#Sta/Elev= 30
       0 1487.17     9.7 1485.32    38.8 1477.47    48.5 1475.21    58.2 1473.42
    67.9 1472.06      97 1468.92     126 1467.23   164.8 1464.47   213.3 1461.96
   271.4 1459.88   319.9 1458.93     436 1457.95   493.3 1457.04   531.5 1456.13
   560.1 1454.45   569.7  1454.3  572.99 1454.61   588.8 1456.32   617.4  1458.4
     627 1460.02   636.5 1462.32   665.2 1470.09   761.4 1495.17   790.2 1501.55
   799.8 1505.81   809.4 1510.91     819 1515.22   828.7 1518.58   857.5 1527.18
#Mann= 3 , 0 , 0
       0      .1       0   560.1    .045       0  572.99      .1       0
#XS Ineff= 2 , 0
          457.66 1460.13
Permanent Ineff=
       F       F
Bank Sta=560.1,572.99
XS Rating Curve= 0 ,0
Exp/Cntr=0.3,0.1

Type RM Length L Ch R = 1 ,6263.7  ,336.3,319.6,302.7
XS GIS Cut Line= 4
     1837997.259      292748.933     1837750.731      291861.781
     1837754.203      291639.558      1837758.11      291374.802
#Sta/Elev= 30
       0 1554.27    68.6 1558.38   146.9  1559.9   186.1 1558.56   215.5  1556.4
   235.1 1554.21   254.7 1551.12   284.1 1542.77   303.7 1537.75   391.8 1519.35
   607.3 1477.18   666.1 1466.82   705.3 1460.82   715.1  1460.2   822.8 1458.82
   920.8 1458.41  1036.7 1455.84  1065.3 1454.29  1075.4 1453.87  1080.3 1454.56
  1094.7 1456.49    1114 1458.09  1123.7 1459.64  1152.8 1466.53  1162.6 1467.84
  1231.3 1472.66  1241.1 1473.93  1250.9 1476.72  1329.4 1503.92  1407.8 1532.03
#Mann= 3 , 0 , 0
       0      .1       0  1065.3    .045       0  1080.3      .1       0
Bank Sta=1065.3,1080.3
XS Rating Curve= 0 ,0
Exp/Cntr=0.3,0.1

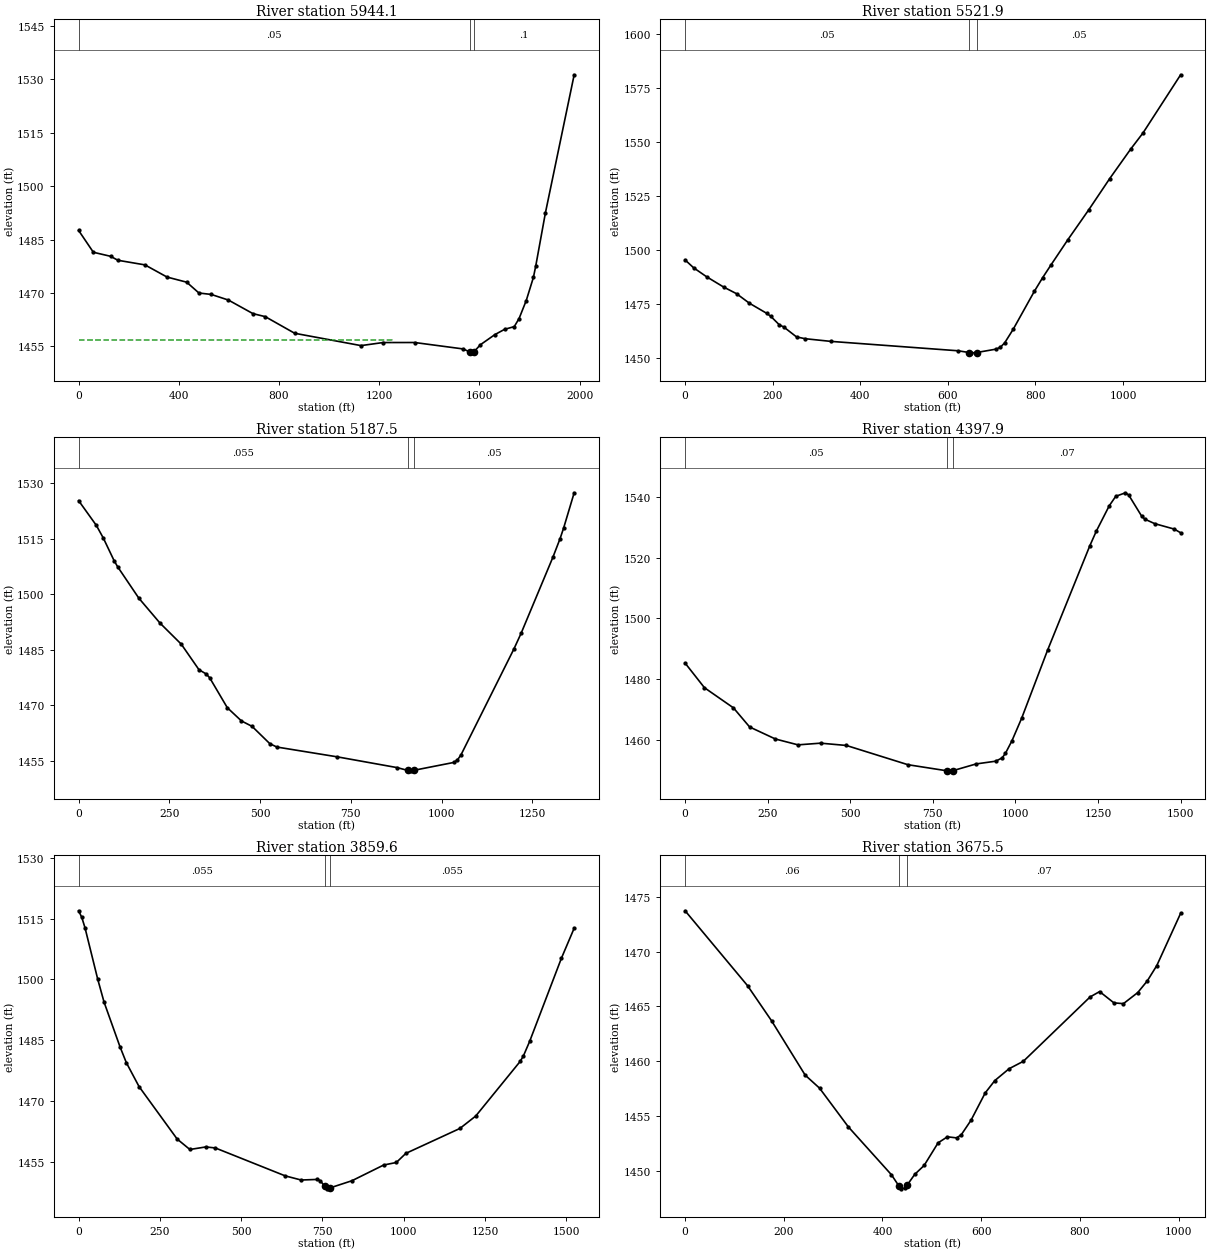
Type RM Length L Ch R = 1 ,5944.1  ,429.1,422.2,415.4
XS GIS Cut Line= 4
     1839221.217      292726.798     1838303.122      291975.411
     1837964.273      291587.909     1837788.492      291373.065
#Sta/Elev= 30
       0 1487.56    58.8 1481.44   127.5 1480.31   156.9 1479.19   264.7  1477.9
     353 1474.48   431.4 1473.04   480.4    1470   529.5  1469.6   598.1 1468.02
   696.1 1464.21   745.2 1463.36   862.8 1458.69  1127.5 1455.23  1215.5 1456.09
  1341.8  1456.1    1536 1454.29 1562.76  1453.4  1574.9  1453.2 1577.62 1453.41
    1604 1455.46  1662.3 1458.33  1701.1 1459.81  1739.4 1460.56  1758.6 1462.82
  1787.3 1467.88    1816  1474.4  1825.6 1477.71  1863.9 1492.52  1978.7 1531.28
#Mann= 3 , 0 , 0
       0     .05       0 1562.76    .045       0 1577.62      .1       0
#XS Ineff= 2 , 0
         1249.72 1456.77
Permanent Ineff=
       F       F
Bank Sta=1562.76,1577.62
XS Rating Curve= 0 ,0
Exp/Cntr=0.3,0.1

Type RM Length L Ch R = 1 ,5521.9  ,330.1,334.3,338.5
XS GIS Cut Line= 4
     1838867.376      291732.223     1838522.324      291491.338
     1838159.911      291269.984     1837923.366      291109.394
#Sta/Elev= 30
       0 1495.48    19.6 1491.83    48.9 1487.72    88.1 1482.91   117.4 1479.85
   146.8 1475.43   185.9  1470.8   195.7 1469.34   215.3 1465.39   225.1 1464.44
   254.4 1459.82     274 1458.99   332.7 1457.75   623.5 1453.39  649.28 1452.56
   652.4 1452.44   665.5 1452.58   710.4 1454.17     720 1455.06   729.7 1457.08
     749 1463.32   797.2 1480.88   816.5 1487.32   835.8  1493.3   874.1 1504.92
   921.7 1518.74   969.4 1533.16    1017 1546.75  1045.6 1554.36  1131.4 1581.28
#Mann= 3 , 0 , 0
       0     .05       0  649.28    .045       0   665.5     .05       0
Bank Sta=649.28,665.5
XS Rating Curve= 0 ,0
Exp/Cntr=0.3,0.1

Type RM Length L Ch R = 1 ,5187.5  ,785.5,789.7,793.9
XS GIS Cut Line= 3
     1839228.404      291734.964     1838720.808      291278.727
     1838213.212      290822.489
#Sta/Elev= 30
       0 1525.31    48.8 1518.63    68.2 1515.17    97.5 1509.14   107.2 1507.49
   165.8 1498.97   224.2 1492.23   282.8 1486.53   331.5 1479.64     351 1478.51
   360.8 1477.49   409.5 1469.38   448.5  1465.8   477.8 1464.33   526.5 1459.67
     546 1458.75   711.8 1456.11   877.5 1453.19   906.8 1452.43   916.5 1452.32
   923.7 1452.47  1033.5 1454.59  1043.2 1455.24    1053 1456.59  1199.2 1485.28
  1218.8 1489.47  1306.5 1510.05    1326 1515.01  1335.8 1517.86    1365 1527.44
#Mann= 3 , 0 , 0
       0    .055       0   906.8    .045       0   923.7     .05       0
Bank Sta=906.8,923.7
XS Rating Curve= 0 ,0
Exp/Cntr=0.3,0.1

Type RM Length L Ch R = 1 ,4397.9  ,531.7,538.2,544.1
XS GIS Cut Line= 4
      1839613.47      291238.734       1839278.4      290782.137
     1839014.512      290464.428     1838641.248      290101.581
#Sta/Elev= 30
       0 1485.28    58.6 1477.15   146.5 1470.49   195.3  1464.2   273.4 1460.23
   341.8  1458.3   410.1 1458.86   488.2  1458.1   674.5 1451.75   792.2 1449.75
   802.4 1449.73   812.2 1449.84     881 1452.01     940 1452.91   959.7 1454.01
   969.5 1455.49   989.2 1459.62  1018.6 1467.06  1097.2 1489.55  1224.9 1523.95
  1244.6 1528.79  1283.8 1537.17  1303.5 1540.29    1333 1541.46  1342.8  1540.7
  1382.1 1533.72  1391.9 1532.74  1421.3 1531.28  1480.3 1529.49  1499.9 1528.27
#Mann= 3 , 0 , 0
       0     .05       0   792.2    .045       0   812.2     .07       0
Bank Sta=792.2,812.2
XS Rating Curve= 0 ,0
Exp/Cntr=0.3,0.1

Type RM Length L Ch R = 1 ,3859.6  ,182.7,184.2,185
XS GIS Cut Line= 4
     1839784.675      291081.999      1839598.19      290382.817
     1839465.177      290078.867      1839200.42      289691.714
#Sta/Elev= 30
       0 1516.97     9.8 1515.31    19.6 1512.77    58.7 1500.08    78.2 1494.41
   127.1 1483.41   146.7 1479.46   185.8 1473.55   303.1 1460.58   342.2    1458
   391.2 1458.63   420.5 1458.38   635.6 1451.48   684.5 1450.46   733.4  1450.6
   743.1  1450.3     757 1448.91   762.7 1448.28   772.4 1448.49   840.7 1450.28
   938.3 1454.16   977.3 1454.79  1006.6 1457.04  1172.7 1463.19  1221.5 1466.26
  1358.3 1479.76  1368.1 1481.09  1387.6 1484.74  1485.3 1505.28  1524.4 1512.67
#Mann= 3 , 0 , 0
       0    .055       0     757    .045       0   772.4    .055       0
Bank Sta=757,772.4
XS Rating Curve= 0 ,0
Exp/Cntr=0.3,0.1

Type RM Length L Ch R = 1 ,3675.5  ,51.7,51.8,51.9
XS GIS Cut Line= 4
     1839963.278      290750.151     1839765.362      290392.512
     1839709.806      290251.887     1839560.501      289833.484
#Sta/Elev= 30
       0 1473.71   126.5 1466.89   175.2 1463.69   243.3 1458.74   272.5 1457.55
   330.9 1454.02   418.2 1449.66   433.3 1448.64   437.1 1448.38   446.6 1448.47
  450.44 1448.75   465.4  1449.7   484.4 1450.51   512.7 1452.57   531.6 1453.12
   550.5 1453.02     560 1453.33   579.3 1454.62   608.2 1457.12   627.6 1458.24
   656.5 1459.32   685.5    1460   820.7 1465.86     840 1466.35     869 1465.32
   888.3 1465.25   917.3 1466.26   936.6 1467.32   955.9 1468.72  1004.2 1473.48
#Mann= 3 , 0 , 0
       0     .06       0   433.3    .045       0  450.44     .07       0
Bank Sta=433.3,450.44
XS Rating Curve= 0 ,0
Exp/Cntr=0.3,0.1

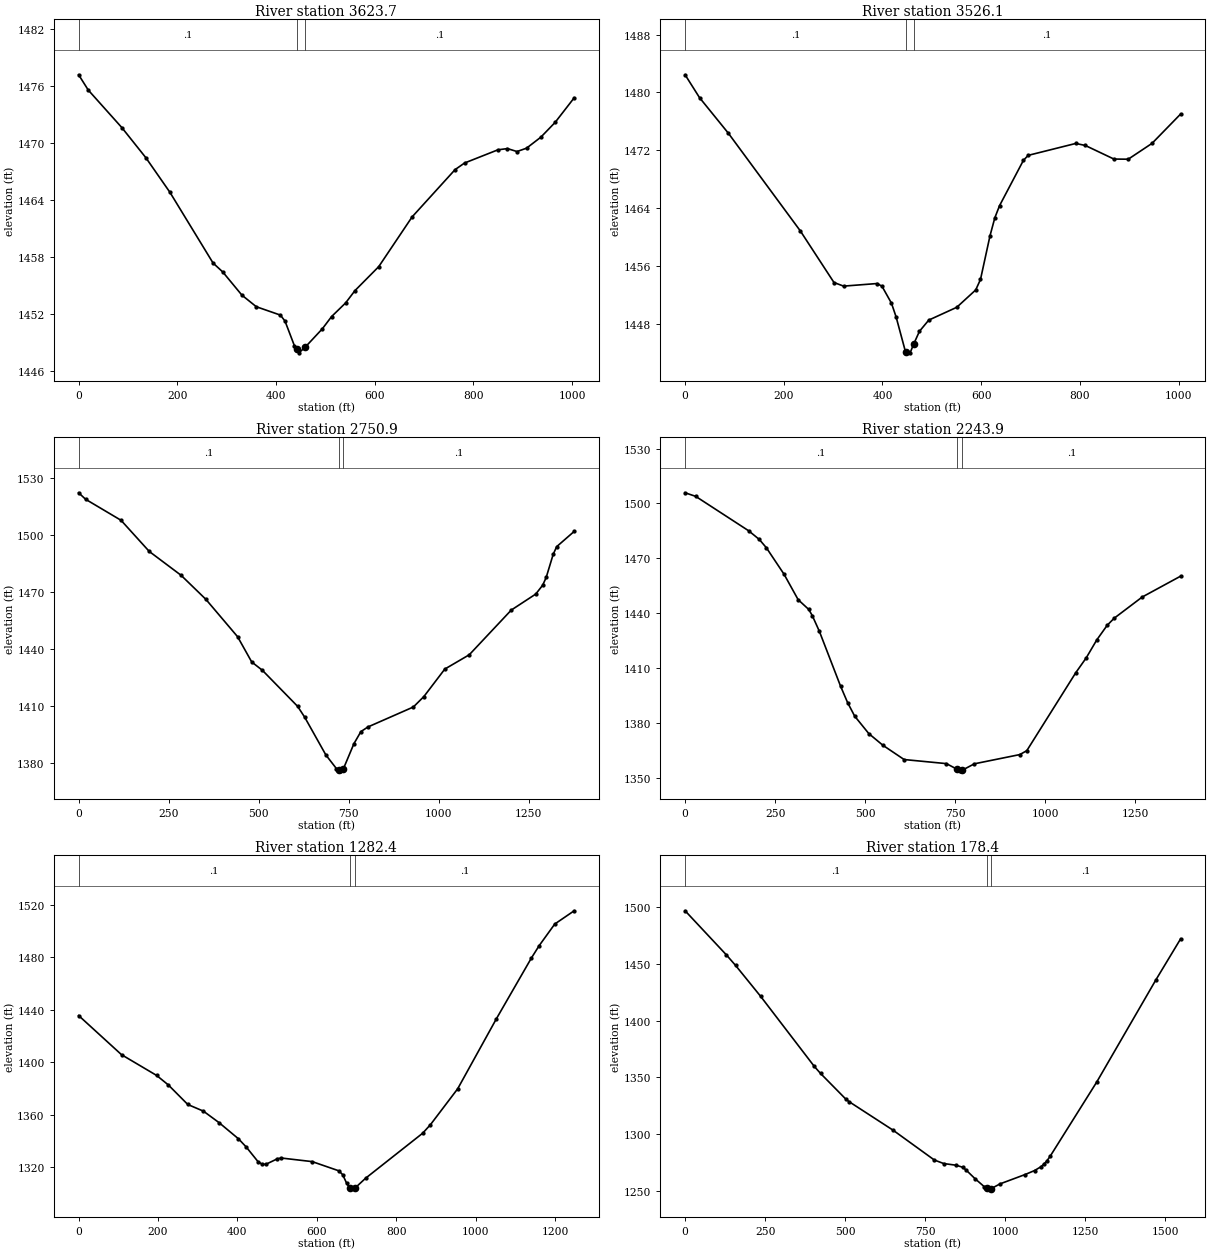
Type RM Length L Ch R = 1 ,3623.7  ,97.6,97.5,97.5
XS GIS Cut Line= 4
     1840011.889      290734.526     1839813.973      290376.887
     1839758.417      290236.262     1839609.112      289817.859
#Sta/Elev= 30
       0 1477.21    19.5  1475.6    87.6 1471.64   136.2 1468.47   184.9 1464.83
   272.5 1457.36     292 1456.43   330.9 1453.98   360.1 1452.76   408.8 1451.88
   418.2 1451.25   437.1 1448.67   441.9 1448.28   446.6  1447.9  459.71 1448.53
   493.8 1450.43   512.7 1451.73     541 1453.16     560 1454.46   608.2 1456.99
   675.8 1462.23   762.8 1467.21   782.1 1467.91   849.7  1469.3     869 1469.43
   888.3 1469.12   907.6 1469.47   936.6 1470.63   965.6 1472.19  1004.2 1474.78
#Mann= 3 , 0 , 0
       0      .1       0   441.9    .045       0  459.71      .1       0
Bank Sta=441.9,459.71
XS Rating Curve= 0 ,0
Exp/Cntr=0.3,0.1

Type RM Length L Ch R = 1 ,3526.1  ,771.9,775.2,778.5
XS GIS Cut Line= 4
     1840088.278      290682.442     1839890.362      290324.804
     1839834.806      290184.179     1839685.501      289765.776
#Sta/Elev= 30
       0 1482.43    29.2 1479.27    87.6 1474.35   233.6 1460.82   301.7 1453.69
   321.2 1453.19   389.3 1453.55     399 1453.17   418.2 1450.83   427.6 1448.93
   446.6 1444.11   447.9 1444.09     456 1443.96   462.9 1445.12   474.9 1446.94
   493.8 1448.49   550.5 1450.26   588.9 1452.66   598.6 1454.11   617.9 1460.16
   627.6 1462.63   637.2 1464.32   685.5 1470.58   695.2 1471.28   791.7 1472.93
     811 1472.65     869 1470.77     898 1470.75   946.2 1472.94  1004.2    1477
#Mann= 3 , 0 , 0
       0      .1       0   447.9    .045       0   462.9      .1       0
Bank Sta=447.9,462.9
XS Rating Curve= 0 ,0
Exp/Cntr=0.3,0.1

Type RM Length L Ch R = 1 ,2750.9  ,503.3,507.1,510.7
XS GIS Cut Line= 3
     1840651.195      290662.539     1840543.467      289974.098
     1840390.192      289311.724
#Sta/Elev= 30
       0 1522.23    19.6 1518.78   117.8 1507.73   196.3  1491.3   284.6 1478.75
   353.3 1466.12   441.6 1446.38   480.9 1433.06   510.4  1428.7   608.5 1409.66
   628.1 1403.94     687 1384.03   716.2 1376.88   722.7  1376.1     726  1375.7
   735.7 1376.84   764.8    1390   784.2 1396.38   803.7 1398.82   929.9 1409.34
   959.1 1414.83  1017.3 1429.33  1085.3 1436.87  1201.9 1460.41  1269.9 1468.85
  1289.3 1473.55    1299 1477.64  1318.4 1489.79  1328.1 1493.84  1376.7 1501.87
#Mann= 3 , 0 , 0
       0      .1       0   722.7    .045       0   735.7      .1       0
Bank Sta=722.7,735.7
XS Rating Curve= 0 ,0
Exp/Cntr=0.3,0.1

Type RM Length L Ch R = 1 ,2243.9  ,954.7,961.4,967.4
XS GIS Cut Line= 3
     1841011.148      290548.562     1841020.593      289851.807
     1840980.759      289173.097
#Sta/Elev= 30
       0 1505.84    29.4 1503.89   176.7 1485.07   206.1 1480.36   225.7 1475.84
   274.8 1461.39   314.1 1447.45   343.5 1442.13   353.3 1438.78     373  1430.2
   431.8 1400.28   451.5 1391.23   471.1 1383.86   510.4 1374.31   549.6 1367.93
   608.5 1360.15     726 1357.92     755 1354.92   764.8 1353.98     770 1354.34
   803.7 1357.82   929.9 1362.86   949.3 1364.99  1085.3 1407.56  1114.5 1415.71
  1143.6 1425.45  1172.7 1433.48  1192.2 1437.35  1269.9  1448.9  1376.7 1460.31
#Mann= 3 , 0 , 0
       0      .1       0     755    .045       0     770      .1       0
Bank Sta=755,770
XS Rating Curve= 0 ,0
Exp/Cntr=0.3,0.1

Type RM Length L Ch R = 1 ,1282.4  ,1116.8,1104,1089.7
XS GIS Cut Line= 4
     1841702.321      290856.332     1841844.682      290325.082
     1841914.127      290016.054     1842000.932      289644.527
#Sta/Elev= 30
       0 1435.55     108 1405.76   196.4 1389.96   225.9 1382.73     275 1367.82
   314.3 1362.76   353.6 1354.03   402.7 1341.68   422.3 1335.41   451.8 1324.33
   461.6 1322.41   471.4 1322.22   500.9 1326.52   510.7 1327.05   588.4 1324.32
   655.6  1317.3   665.2 1314.34   674.8 1308.07  682.38 1304.52   684.4 1303.59
   695.8 1304.08   722.8 1311.64   866.7 1345.96   886.3 1352.47   954.8 1379.76
  1052.6 1433.23  1140.6  1479.4  1160.2 1488.82  1199.4 1505.24  1248.3 1515.34
#Mann= 3 , 0 , 0
       0      .1       0  682.38    .045       0   695.8      .1       0
Bank Sta=682.38,695.8
XS Rating Curve= 0 ,0
Exp/Cntr=0.3,0.1

Type RM Length L Ch R = 1 ,178.4   ,173.4,178.4,184.5
XS GIS Cut Line= 5
     1842950.585      291206.159     1842967.946      290556.853
     1842978.363      290428.381     1842846.418      290101.992
     1842686.696      289716.575
#Sta/Elev= 30
       0 1496.68   127.9 1458.13   157.5 1448.59   236.2 1421.19   403.5 1359.56
   423.2 1353.31   501.9 1330.77   511.8 1328.56   649.5 1303.37   778.4 1277.08
   807.8 1273.96   846.9 1272.46   866.4 1270.74   876.2 1268.63   905.6  1260.6
   934.9 1253.45   941.5 1252.31   944.7 1251.75   954.5 1251.68   956.5 1251.96
   983.8 1256.07    1062 1264.29  1091.4 1267.79  1110.9 1271.06  1120.7 1273.44
  1130.5 1276.53  1140.2  1280.4  1285.7 1345.81  1470.1 1435.67  1547.7 1471.98
#Mann= 3 , 0 , 0
       0      .1       0   941.5    .045       0   956.5      .1       0
Bank Sta=941.5,956.5
XS Rating Curve= 0 ,0
Exp/Cntr=0.3,0.1

Chan Stop Cuts=-1
Use User Specified Reach Order=0
Composite Channel Slope=5